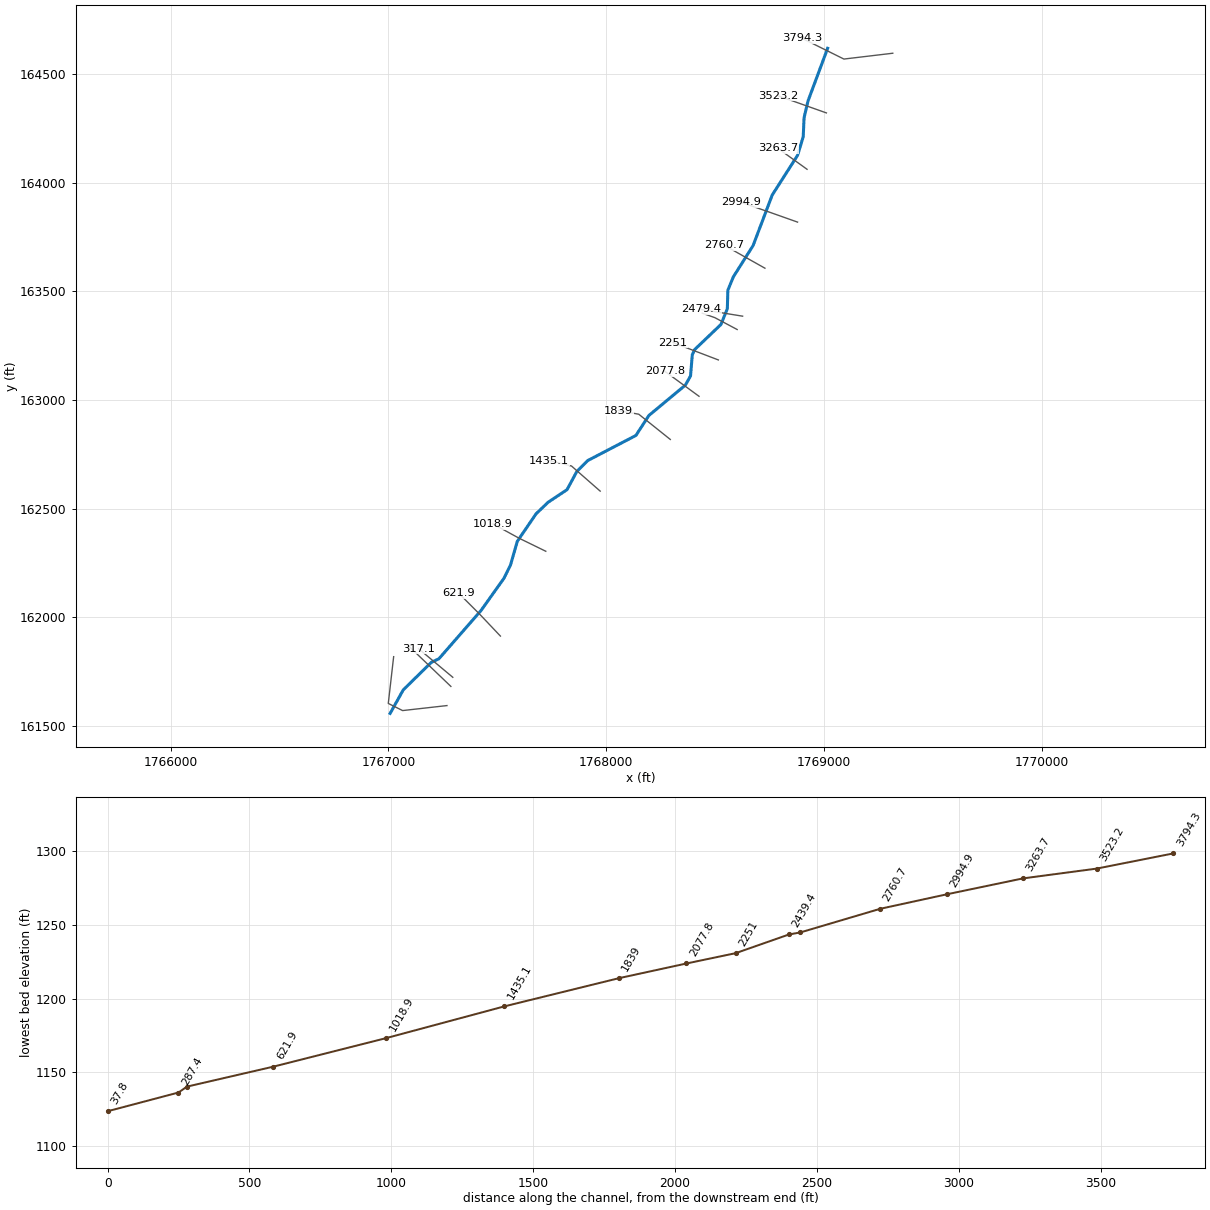
--- Shabbyroom Branch.prj (project) ---

Proj Title=Shabbyroom Branch
Current Plan=p01
Default Exp/Contr=0,0
English Units
Geom File=g01
Flow File=f01
Plan File=p01
BEGIN DESCRIPTION:
END DESCRIPTION:
DSS Export Rating Curves= 0
DSS Export Rating Curve Sorted= 0
DSS Export Volume Flow Curves= 0
DXF OffsetX= 0
DXF OffsetY= 0
DXF ScaleX= 0
DXF ScaleY= 0

--- Shabbyroom Branch.p01 (plan) ---

Plan Title=Floodplain
Program Version=4.00
Geom File=g01
Flow File=f01
K Sum by GR=0
Std Step Tol=0.01
Critical Tol=0.01
Num of Std Step Trials=20
Max Error Tol=0.3
Flow Tol Ratio=0.001
Split Flow NTrial=30
Split Flow Tol=0.02
Split Flow Ratio=0.02
Log Output Level=0
Friction Slope Method=1
Unsteady Friction Slope Method=2
Unsteady Bridges Friction Slope Method=1
Global Log Level=0
CheckData=False
Run HTab=0
Run UNet=0
Run PostProcess=0
UNET Theta=0
UNET Theta Warmup=0
UNET ZTol=0
UNET ZSATol=0
UNET MxIter=0
UNET MaxInSteps=0
UNET DtIC=0
UNET DtMin=0
UNET MaxCRTS=0
UNET WFStab=0
UNET SFStab=0
UNET WFX=0
UNET SFX=0
UNET DSS MLevel=0
UNET DZMax Abort=0
UNET Convert EG Bridges=0
UNET Use Existing IB Tables=0
UNET Froude Limit=0
UNET Froude Power=0
Write IC File=0
Echo Input=False
Echo Output=False
Write Detailed=0

--- Shabbyroom Branch.f01 (steady flow) ---

Flow Title=NFF Regression Equation
Program Version=4.00
Number of Profiles=1
Profile Names=P100yr
River Rch & RM=Shabbyroom Br...,Main      ,3794.3
577.0614
River Rch & RM=Shabbyroom Br...,Main      ,3263.7
593.0089
River Rch & RM=Shabbyroom Br...,Main      ,2077.8
652.0345
River Rch & RM=Shabbyroom Br...,Main      ,287.4
687.2702
Boundary for River Rch & Prof#=Shabbyroom Br...,Main      ,1
Up Type=0
Dn Type=3
Dn Slope=0.07708

--- Shabbyroom Branch.g01 (geometry) ---

Geom Title=Geometry
Program Version=4.00

River Reach=Shabbyroom Br...,Main
Reach XY= 30
     1769015.958      164617.723     1768925.743      164374.746
     1768907.912      164298.705      1768903.91      164210.503
     1768877.847      164125.125     1768761.526      163942.481
     1768673.975      163710.439     1768583.271      163566.443
        1768558.      163504.845     1768555.598      163419.701
     1768526.229      163347.179     1768406.004      163232.146
     1768394.774      163208.438     1768386.598      163110.118
     1768362.603      163067.836     1768195.216      162928.378
     1768135.919      162836.661     1767915.482      162721.585
     1767864.303       162670.36       1767819.8      162587.428
     1767732.825      162529.301     1767677.712      162476.341
     1767591.602      162349.936     1767560.136      162240.331
     1767529.719      162178.973     1767424.854      162031.346
     1767231.804       161809.71     1767196.294      161792.582
     1767067.728      161666.058     1767007.781      161558.244

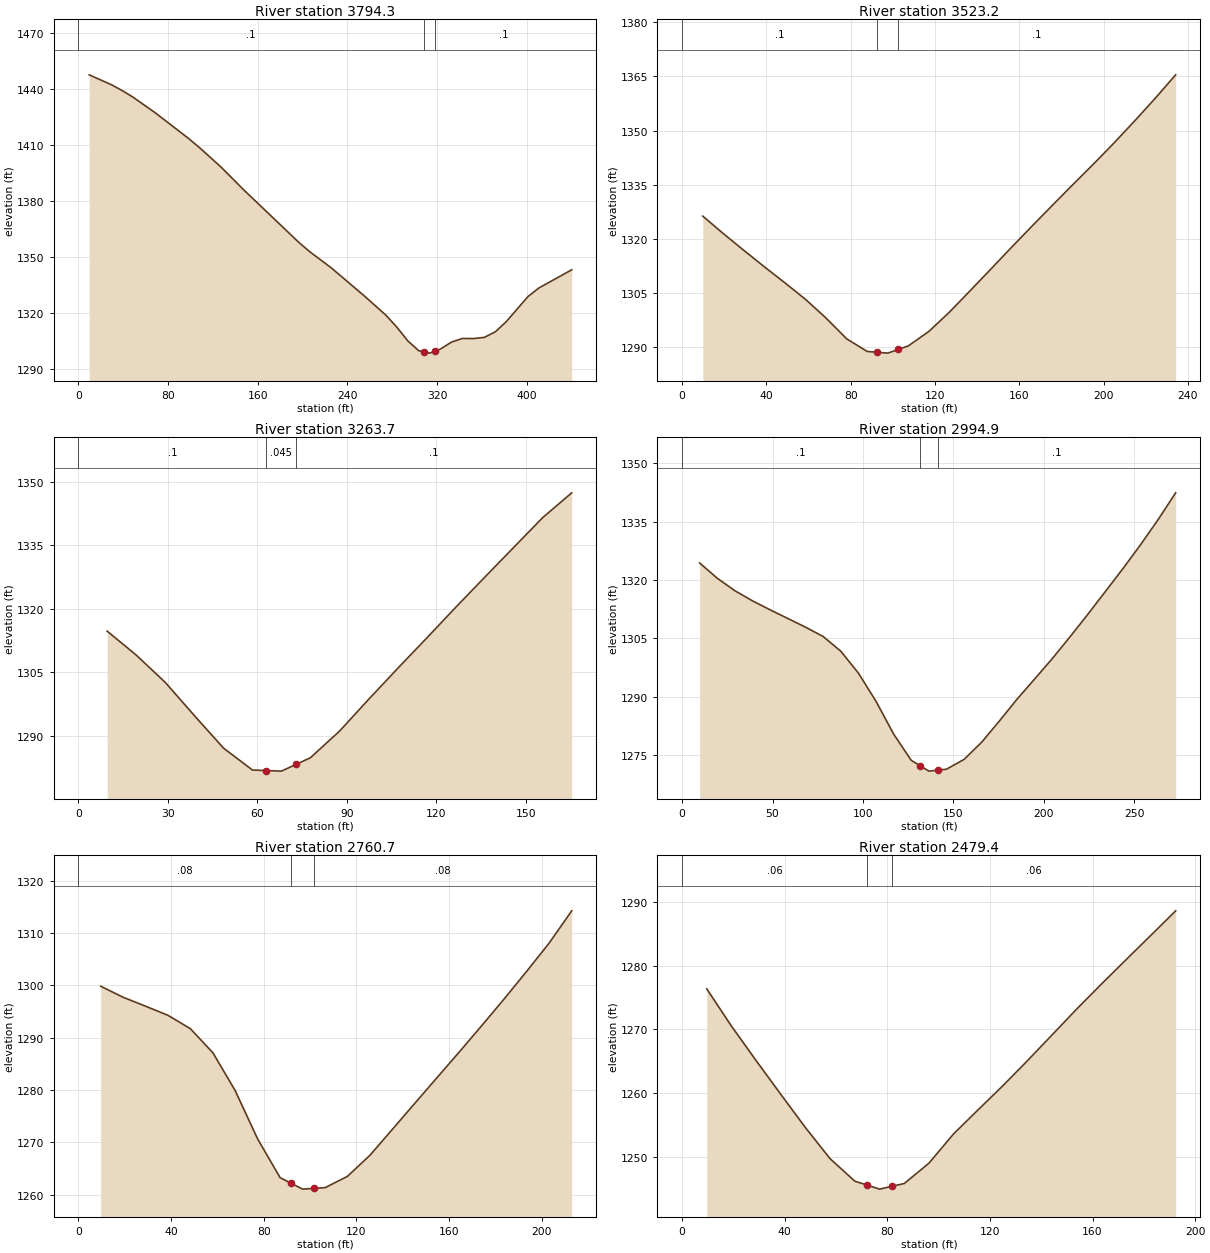
Type RM Length L Ch R = 1 ,3794.3  ,268.7,271.1,273.5
XS GIS Cut Line= 4
      1769315.12       164594.96     1769090.664      164568.175
      1769021.11      164602.744     1768898.875      164663.496
#Sta/Elev= 30
     9.8 1447.44    29.5 1442.18    39.3 1439.01    49.1 1435.42    68.8  1427.1
    98.3  1413.5   108.1 1408.57   127.8 1397.92   147.4 1386.09   196.6 1357.99
   206.4 1352.95     226 1344.14   255.2 1329.27   274.6  1318.9   284.3 1312.52
     294 1305.22   303.7 1300.01   308.5 1299.37   313.5  1298.7   318.5 1299.84
   323.2 1300.92     333 1304.62   342.7 1306.54   352.5 1306.48   362.2 1307.11
     372 1310.07   381.7 1315.46   401.2 1328.95     411 1333.56   440.2 1343.25
#Mann= 3 , 0 , 0
       0      .1       0   308.5    .045       0   318.5      .1       0
Bank Sta=308.5,318.5
XS Rating Curve= 0 ,0
Exp/Cntr=0.3,0.1

Type RM Length L Ch R = 1 ,3523.2  ,265.3,259.5,253.8
XS GIS Cut Line= 2
     1769010.252      164320.421     1768789.581      164398.907
#Sta/Elev= 26
     9.8  1326.3    19.5 1321.48    29.3 1316.81      39 1312.27    48.8 1307.81
    58.6 1303.22    68.3 1298.06    78.1 1292.31    87.8 1288.82    92.6 1288.59
    97.6 1288.35   102.6 1289.38   107.3 1290.34   117.1 1294.37   126.9 1299.74
   136.6  1305.6   146.4 1311.57   156.1 1317.54   165.9 1323.46   175.7  1329.3
   185.4 1335.03   195.2 1340.73   204.9 1346.54   214.7 1352.65   224.5 1358.95
   234.2 1365.45
#Mann= 3 , 0 , 0
       0      .1       0    92.6    .045       0   102.6      .1       0
Bank Sta=92.6,102.6
XS Rating Curve= 0 ,0
Exp/Cntr=0.3,0.1

Type RM Length L Ch R = 1 ,3263.7  ,263,268.8,274.6
XS GIS Cut Line= 2
     1768921.528      164061.076     1768787.306      164157.762
#Sta/Elev= 19
     9.7 1314.75    19.5 1309.06    29.2 1302.63    38.9 1294.83    48.7 1287.13
    58.4 1281.96    63.1 1281.83    68.1  1281.7    73.1 1283.32    77.8 1284.85
    87.6 1291.16    97.3 1298.62     107  1305.9   116.8 1313.12   126.5 1320.36
   136.2 1327.45     146 1334.55   155.7 1341.57   165.4  1347.4
#Mann= 3 , 0 , 0
       0      .1       0    63.1    .045       0    73.1      .1       0
Bank Sta=63.1,73.1
XS Rating Curve= 0 ,0
Exp/Cntr=0.3,0.1

Type RM Length L Ch R = 1 ,2994.9  ,237.8,234.2,230.7
XS GIS Cut Line= 3
     1768877.935      163818.114     1768749.294       163863.75
     1768620.364      163908.604
#Sta/Elev= 30
     9.7 1324.39    19.5 1320.44    29.2 1317.25      39 1314.63    48.7 1312.34
    58.5 1310.11    68.2  1307.9      78 1305.49    87.7 1301.74    97.5 1296.09
   107.2 1288.86     117  1280.4   126.7 1273.66   131.5 1272.29   136.5 1270.87
   141.5 1271.12   146.2 1271.36     156  1273.9   165.7 1278.31   175.5 1283.77
   185.2 1289.34     195 1294.56   204.8 1299.83   214.5 1305.37   224.3 1311.12
     234 1316.98   243.8 1322.92   253.5 1329.03   263.3 1335.54     273 1342.43
#Mann= 3 , 0 , 0
       0      .1       0   131.5    .045       0   141.5      .1       0
Bank Sta=131.5,141.5
XS Rating Curve= 0 ,0
Exp/Cntr=0.3,0.1

Type RM Length L Ch R = 1 ,2760.7  ,274.2,281.2,288.3
XS GIS Cut Line= 2
     1768728.157      163606.085     1768542.748      163710.733
#Sta/Elev= 24
     9.7 1299.85    19.4 1297.73      29 1296.04    38.7 1294.29    48.4 1291.72
    58.1 1287.12    67.7  1279.9    77.4 1270.64    87.1 1263.23    91.8 1262.17
    96.8 1261.04   101.8 1261.19   106.5 1261.32   116.1 1263.47   125.8 1267.49
   135.5 1272.46   145.2 1277.45   154.8 1282.37   164.5 1287.33   174.2 1292.37
   183.9  1297.5   193.5 1302.72   203.2 1308.13   212.9 1314.27
#Mann= 3 , 0 , 0
       0     .08       0    91.8    .045       0   101.8     .08       0
Bank Sta=91.8,101.8
XS Rating Curve= 0 ,0
Exp/Cntr=0.3,0.1

Type RM Length L Ch R = 1 ,2479.4  ,46.8,40,33.2
XS GIS Cut Line= 2
     1768625.784      163385.414     1768435.825      163416.126
#Sta/Elev= 22
     9.6 1276.36    19.2 1270.54    28.9 1265.09    38.5 1259.82    48.1 1254.61
    57.7 1249.75    67.3 1246.24      72 1245.64      77 1244.99      82 1245.45
    86.6 1245.87    96.2 1249.05   105.8 1253.63   115.5 1257.46   125.1 1261.21
   134.7 1265.14   144.3 1269.18   153.9 1273.23   163.6 1277.16   173.2 1280.98
   182.8 1284.77   192.4 1288.58
#Mann= 3 , 0 , 0
       0     .06       0      72    .045       0      82     .06       0
Bank Sta=72,82
XS Rating Curve= 0 ,0
Exp/Cntr=0.3,0.1

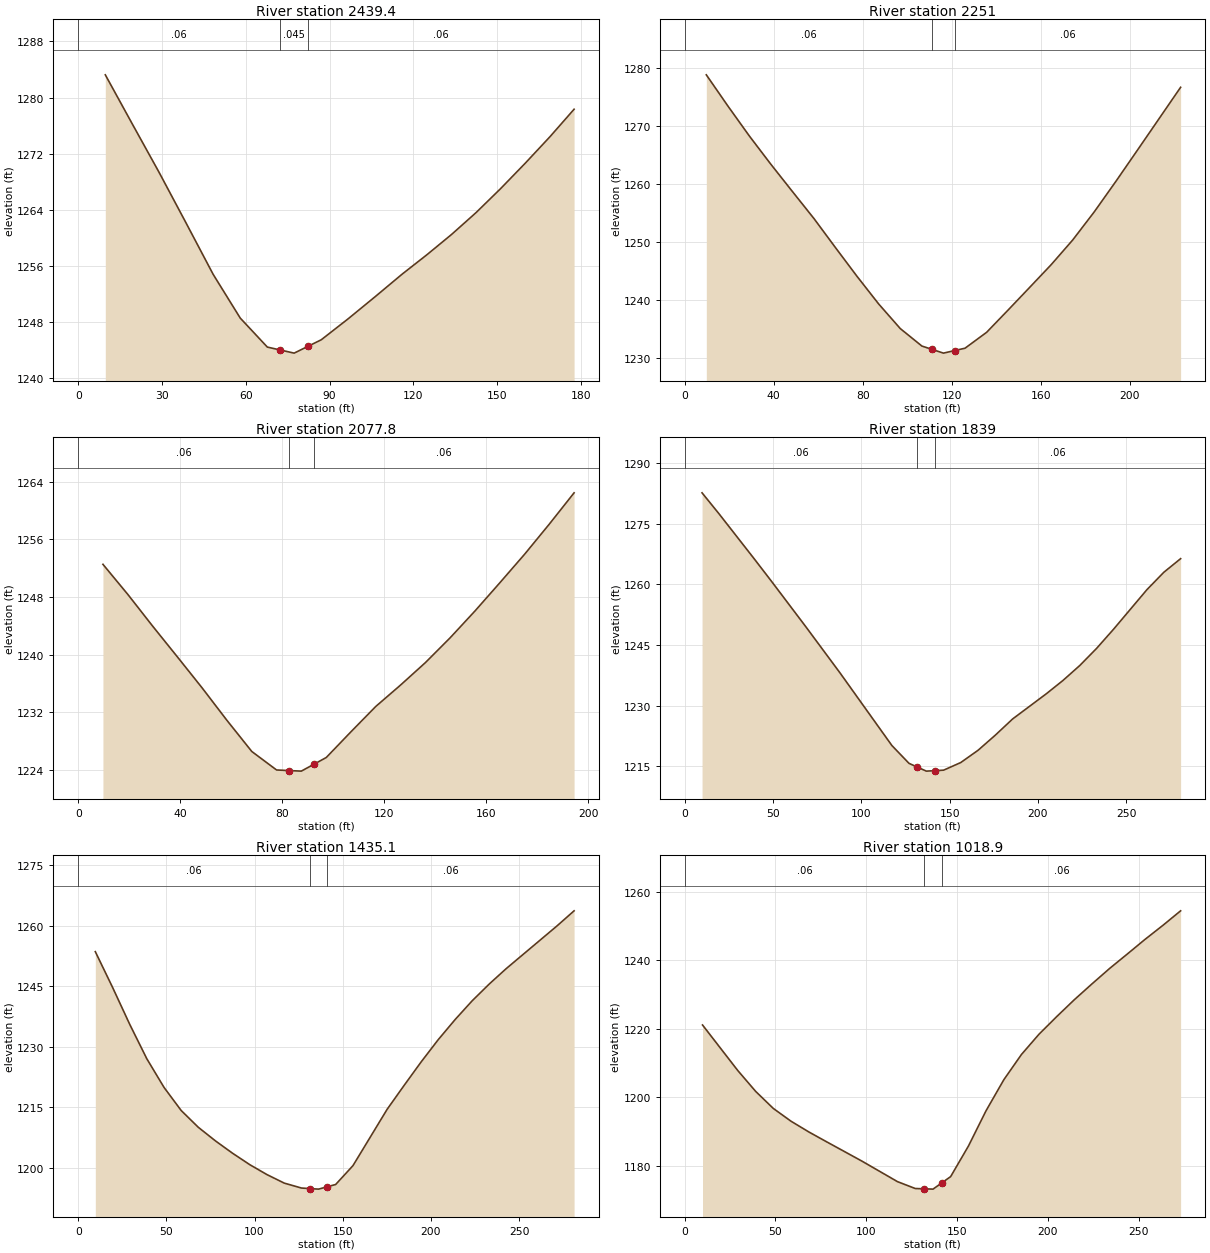
Type RM Length L Ch R = 1 ,2439.4  ,186.1,188.4,190.7
XS GIS Cut Line= 3
     1768600.759       163323.99     1768498.386      163378.589
     1768440.375      163399.064
#Sta/Elev= 21
     9.7 1283.23    19.3 1276.28      29 1269.31    38.7 1262.07    48.3 1254.83
      58  1248.6    67.7 1244.47    72.3 1244.06    77.3 1243.61    82.3 1244.59
      87 1245.51    96.7 1248.52   106.4 1251.68     116 1254.87   124.8 1257.61
   133.6 1260.49   142.4 1263.61   151.2 1267.03     160 1270.64   168.8 1274.39
   177.5 1278.33
#Mann= 3 , 0 , 0
       0     .06       0    72.3    .045       0    82.3     .06       0
Bank Sta=72.3,82.3
XS Rating Curve= 0 ,0
Exp/Cntr=0.3,0.1

Type RM Length L Ch R = 1 ,2251    ,178.6,173.2,167.9
XS GIS Cut Line= 2
     1768514.311       163184.08     1768306.153      163263.704
#Sta/Elev= 25
     9.7 1278.89    19.4 1273.51    29.1 1268.31    38.8 1263.42    48.4 1258.76
    58.1 1254.09    67.8 1249.06    77.5  1244.1    87.2 1239.35    96.9 1235.11
   106.6  1232.1   111.3 1231.51   116.3 1230.88   121.3 1231.32     126 1231.73
   135.7 1234.47   145.3 1238.29     155  1242.2   164.7 1246.13   174.4  1250.4
   184.1 1255.26   193.8 1260.51   203.5  1265.9   213.2 1271.32   222.9 1276.74
#Mann= 3 , 0 , 0
       0     .06       0   111.3    .045       0   121.3     .06       0
Bank Sta=111.3,121.3
XS Rating Curve= 0 ,0
Exp/Cntr=0.3,0.1

Type RM Length L Ch R = 1 ,2077.8  ,239.7,238.8,237.8
XS GIS Cut Line= 2
     1768425.588      163016.871     1768268.616      163131.756
#Sta/Elev= 22
     9.7 1252.54    19.5 1248.35    29.2 1243.97    38.9 1239.71    48.6 1235.41
    58.4 1230.88    68.1 1226.59    77.8 1224.03    82.5 1223.95    87.5 1223.87
    92.5 1224.83    97.3 1225.76     107 1229.33   116.7 1232.83   126.4 1235.79
   136.2 1238.92   145.9 1242.36   155.6 1246.06   165.3 1249.95   175.1 1253.94
   184.8 1258.12   194.5 1262.45
#Mann= 3 , 0 , 0
       0     .06       0    82.5    .045       0    92.5     .06       0
Bank Sta=82.5,92.5
XS Rating Curve= 0 ,0
Exp/Cntr=0.3,0.1

Type RM Length L Ch R = 1 ,1839    ,404.8,403.9,403
XS GIS Cut Line= 3
     1768293.805      162818.264     1768148.947      162934.395
     1768055.363      162951.347
#Sta/Elev= 24
     9.8 1282.61    19.5 1277.38    39.1 1266.44    48.9 1260.88    68.4 1249.62
    87.9 1238.13   117.3 1220.17     127 1215.76   131.8 1214.82   136.8 1213.84
   141.8 1213.96   146.6 1214.08   156.3 1215.96   166.1 1218.99   175.9 1222.74
   185.7 1226.74   204.7 1232.94   214.2 1236.25   223.7 1239.94   233.2 1244.16
   242.7 1248.84   261.7 1258.67   271.3 1262.98   280.8 1266.34
#Mann= 3 , 0 , 0
       0     .06       0   131.8    .045       0   141.8     .06       0
Bank Sta=131.8,141.8
XS Rating Curve= 0 ,0
Exp/Cntr=0.3,0.1

Type RM Length L Ch R = 1 ,1435.1  ,410.9,416.2,420.5
XS GIS Cut Line= 3
      1767971.85      162580.633     1767840.158      162696.233
     1767737.165      162721.359
#Sta/Elev= 28
     9.7 1253.57    19.5  1244.7    29.2 1235.56    38.9 1227.01    48.7 1219.88
    58.4 1214.17    68.1 1210.01    77.9 1206.61    87.6 1203.55    97.4 1200.71
   107.1 1198.26   116.8 1196.17   126.6 1194.94   131.3 1194.81   136.3 1194.67
   141.3 1195.27     146 1195.82   155.8 1200.49   175.2 1214.48   184.9 1220.45
   194.5 1226.24   204.1 1231.71   213.8 1236.76   223.4 1241.38   233.1 1245.55
   242.7 1249.36   271.6 1259.99   281.2  1263.7
#Mann= 3 , 0 , 0
       0     .06       0   131.3    .045       0   141.3     .06       0
Bank Sta=131.3,141.3
XS Rating Curve= 0 ,0
Exp/Cntr=0.3,0.1

Type RM Length L Ch R = 1 ,1018.9  ,404,397.1,391.3
XS GIS Cut Line= 3
     1767722.208      162303.962     1767599.371      162364.103
     1767479.727      162429.713
#Sta/Elev= 30
     9.8 1221.09    19.5 1214.44    29.3 1207.73    39.1 1201.67    48.8  1196.7
    58.6 1192.95    68.4 1189.82    78.2 1186.94    87.9 1184.13    97.7 1181.28
   107.5 1178.28   117.2 1175.31     127  1173.3   131.8 1173.21   136.8 1173.12
   141.8 1175.01   146.5 1176.78   156.3 1185.71     166 1196.02   175.8 1205.09
   185.5 1212.46   195.2  1218.4     205 1223.57   214.7  1228.5   224.5 1233.16
   234.2 1237.66     244  1241.9   253.7 1246.15   263.5 1250.23   273.2 1254.45
#Mann= 3 , 0 , 0
       0     .06       0   131.8    .045       0   141.8     .06       0
Bank Sta=131.8,141.8
XS Rating Curve= 0 ,0
Exp/Cntr=0.3,0.1

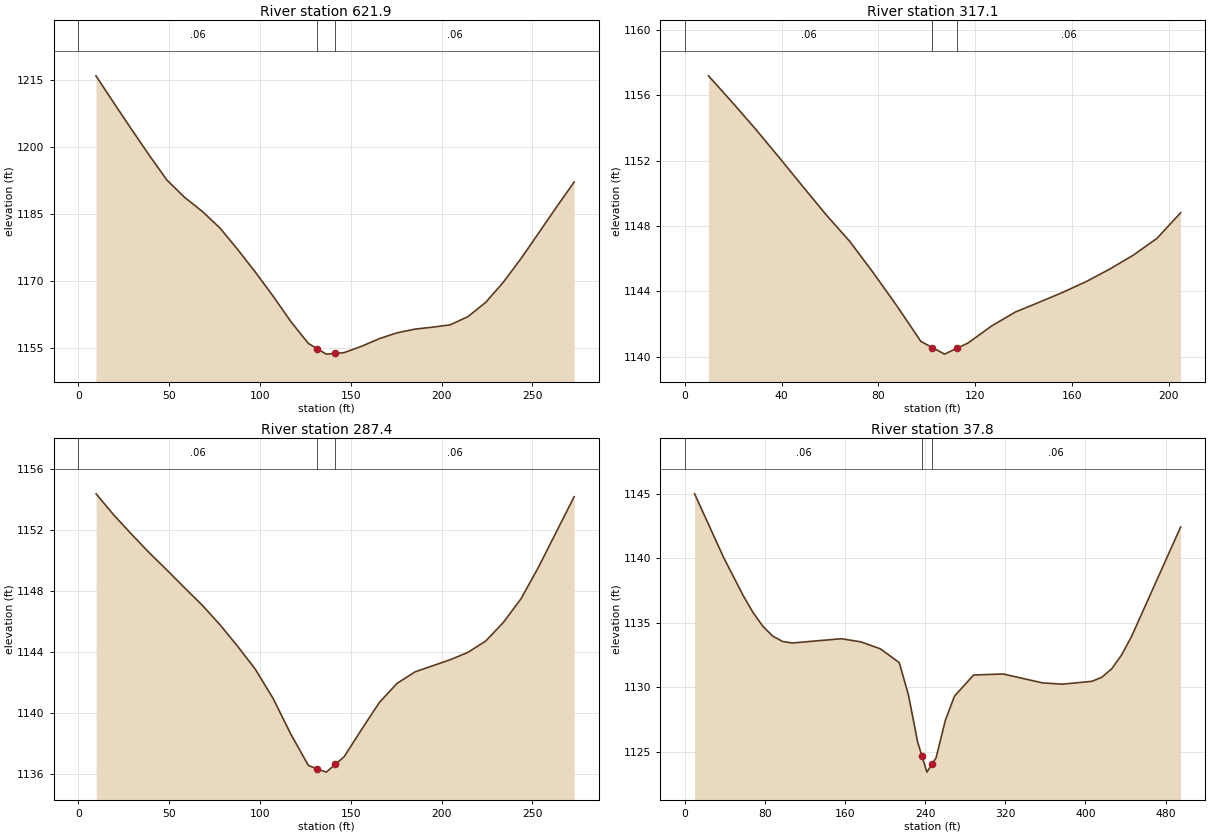
Type RM Length L Ch R = 1 ,621.9   ,302.2,304.8,307
XS GIS Cut Line= 3
     1767513.877      161913.847     1767420.104      162013.025
     1767323.713      162109.754
#Sta/Elev= 30
     9.7  1215.9    19.5 1209.89    29.2 1204.01      39 1198.19    48.7 1192.66
    58.5 1188.76    68.2 1185.64      78  1181.9    87.7 1177.13    97.5 1172.04
   107.2 1166.72     117 1161.02   126.7 1156.12   131.5 1154.96   136.5 1153.74
   141.5  1153.9   146.2 1154.05     156  1155.5   165.8 1157.21   175.5  1158.5
   185.3 1159.32     195 1159.76   204.8 1160.29   214.5 1162.11   224.3  1165.3
     234  1169.8   243.8 1175.12   253.5 1180.81   263.3  1186.6     273 1192.18
#Mann= 3 , 0 , 0
       0     .06       0   131.5    .045       0   141.5     .06       0
Bank Sta=131.5,141.5
XS Rating Curve= 0 ,0
Exp/Cntr=0.3,0.1

Type RM Length L Ch R = 1 ,317.1   ,31.3,29.7,28.1
XS GIS Cut Line= 2
     1767295.269      161724.218     1767138.133      161855.845
#Sta/Elev= 23
     9.8  1157.2    19.5  1155.6    29.3 1153.93      39  1152.2    48.8 1150.42
    58.6 1148.66    68.3 1147.04    78.1  1145.1    87.8 1143.08    97.6 1140.93
   102.4 1140.55   107.4 1140.15   112.4  1140.5   117.1 1140.83   126.9 1141.88
   136.7 1142.73   146.4 1143.32   156.2 1143.93   165.9 1144.59   175.7 1145.36
   185.5 1146.22   195.2 1147.24     205 1148.81
#Mann= 3 , 0 , 0
       0     .06       0   102.4    .045       0   112.4     .06       0
Bank Sta=102.4,112.4
XS Rating Curve= 0 ,0
Exp/Cntr=0.3,0.1

Type RM Length L Ch R = 1 ,287.4   ,243.5,249.7,255.8
XS GIS Cut Line= 3
     1767286.551      161682.245     1767188.055      161776.748
     1767089.559       161871.25
#Sta/Elev= 30
     9.8 1154.37    19.5 1152.99    29.2 1151.74      39 1150.52    48.8 1149.38
    58.5 1148.22    68.3 1147.07      78  1145.8    87.7 1144.39    97.5 1142.88
   107.3 1140.96     117 1138.64   126.7 1136.58   131.5 1136.37   136.5 1136.15
   141.5 1136.66   146.3 1137.15     156 1138.95   165.8 1140.72   175.5 1141.96
   185.3 1142.71     195 1143.11   204.8 1143.51   214.5 1143.99   224.3 1144.73
     234 1145.95   243.8 1147.51   253.5  1149.6   263.2 1151.88     273 1154.18
#Mann= 3 , 0 , 0
       0     .06       0   131.5    .045       0   141.5     .06       0
Bank Sta=131.5,141.5
XS Rating Curve= 0 ,0
Exp/Cntr=0.3,0.1

Type RM Length L Ch R = 1 ,37.8    ,44.1,37.8,31.4
XS GIS Cut Line= 4
     1767268.568      161594.117     1767064.899      161571.122
     1766999.199      161603.972     1767023.836      161819.139
#Sta/Elev= 30
     9.8 1144.98      39 1140.01    58.6 1137.06    68.3 1135.77    78.1 1134.71
    87.8 1133.96    97.6 1133.55   107.4 1133.43   156.2 1133.76   175.7 1133.52
   195.2 1132.98   214.1 1131.91   223.3  1129.4   232.5 1125.75   236.7 1124.69
   241.7 1123.43   246.7 1124.03   250.9 1124.54   260.1 1127.44   269.2 1129.31
   288.3 1130.95   317.8 1131.03   357.2 1130.34   376.9 1130.24   406.4 1130.46
   416.2 1130.77   426.1 1131.42   435.9 1132.48   445.8  1133.9     495 1142.41
#Mann= 3 , 0 , 0
       0     .06       0   236.7    .045       0   246.7     .06       0
Bank Sta=236.7,246.7
XS Rating Curve= 0 ,0
Exp/Cntr=0.3,0.1

Chan Stop Cuts=-1
Use User Specified Reach Order=0